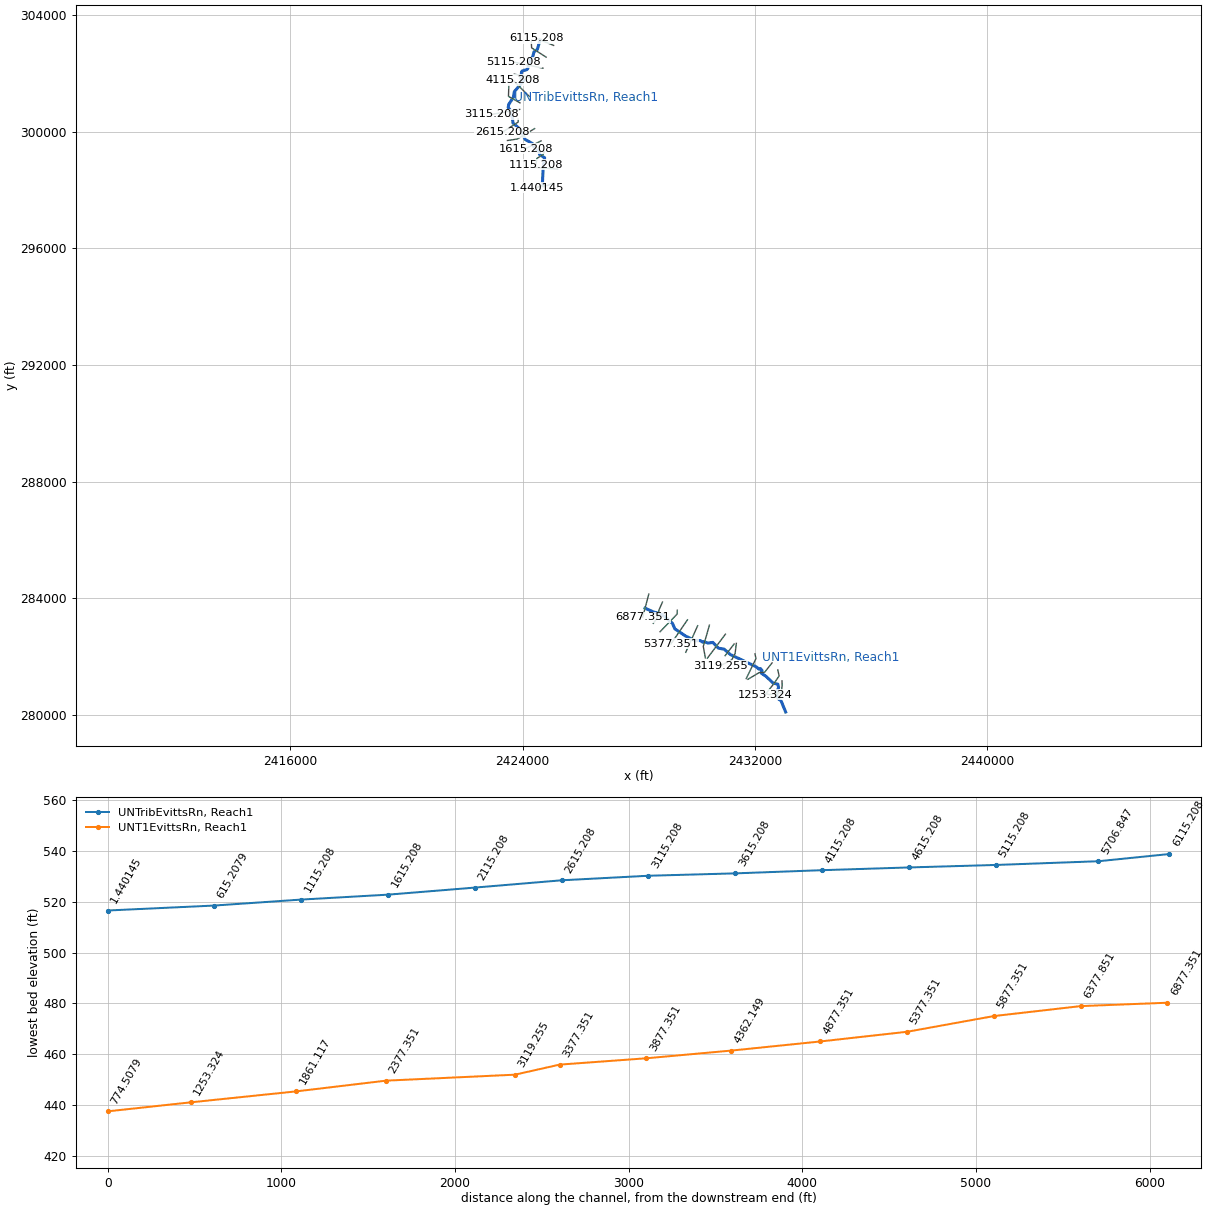
--- UnnamedTribToEvitts.prj (project) ---

Proj Title=UnnamedTribToEvittsRun
Current Plan=p01
Default Exp/Contr=0.3,0.1
English Units
Geom File=g01
Flow File=f01
Plan File=p01
Y Axis Title=Elevation
X Axis Title(PF)=Main Channel Distance
X Axis Title(XS)=Station
BEGIN DESCRIPTION:
END DESCRIPTION:
DSS Export Rating Curves= 0
DSS Export Rating Curve Sorted= 0
DSS Export Volume Flow Curves= 0
DXF OffsetX= 0
DXF OffsetY= 0
DXF ScaleX= 1
DXF ScaleY= 10

--- UnnamedTribToEvitts.p01 (plan) ---

Plan Title=UnnamedTribToEvittsRun
Program Version=4.10
Short Identifier=UnnamedTribT
Geom File=g01
Flow File=f01
Subcritical Flow
K Sum by GR= 0
Std Step Tol= 0.01
Critical Tol= 0.01
Num of Std Step Trials= 20
Max Error Tol= 0.3
Flow Tol Ratio= 0.001
Split Flow NTrial= 30
Split Flow Tol= 0.02
Split Flow Ratio= 0.02
Log Output Level= 0
Friction Slope Method= 1
Unsteady Friction Slope Method= 2
Unsteady Bridges Friction Slope Method= 1
Parabolic Critical Depth
Global Vel Dist= 0 , 0 , 0
Global Log Level= 0
CheckData=True
Encroach Param=-1 ,0,0, 0
Computation Interval=1HOUR
Output Interval=1HOUR
Run HTab= 0
Run UNet= 0
Run PostProcess= 0
Run WQNet= 0
UNET Theta= 1
UNET Theta Warmup= 1
UNET ZTol= 0.02
UNET ZSATol= 0.05
UNET MxIter= 20
UNET MaxInSteps= 0
UNET DtIC= 0
UNET DtMin= 0
UNET MaxCRTS= 20
UNET WFStab= 2
UNET SFStab= 1
UNET WFX= 1
UNET SFX= 1
UNET DSS MLevel= 4
UNET DZMax Abort= 100
UNET Convert EG Bridges= 0
UNET Use Existing IB Tables=-1
UNET Froude Reduction=False
UNET Froude Limit= 1
UNET Froude Power= 10
UNET Time Slicing=0,0, 5
UNET Junction Losses=0
Instantaneous Interval=1HOUR
Write IC File= 0
Write IC File at Sim End=0
Echo Input=False
Echo Parameters=False
Echo Output=False
Write Detailed= 0
WQ AD Non Conservative
WQ ULTIMATE=-1
WQ Max Comp Step=1HOUR
WQ Output Interval=15MIN
WQ Output Selected Increments= 0
WQ Output face flow=0
WQ Output face velocity=0
WQ Output face area=0
WQ Output face dispersion=0
WQ Output cell volume=0
WQ Output cell surface area=0
WQ Output cell continuity=0
WQ Output cumulative cell continuity=0
WQ Output face conc=0
WQ Output face dconc_dx=0
WQ Output face courant=0
WQ Output face peclet=0
WQ Output face adv mass=0
WQ Output face disp mass=0
WQ Output cell mass=0
WQ Output cell source sink temp=0
WQ Output cell source sink nsm=0
WQ Output MaxMinRange=-1
WQ Daily Max Min Mean=-1
WQ Daily Range=0
WQ Daily Time=0
WQ Create Restart=0
WQ Fixed Restart=0
WQ System Summary=0
WQ Use Fixed Temperature=0
Sorting and Armoring Iterations= 10
XS Update Threshold= 0.02
Hydraulics Update Threshold= 0.02
Energy Slope Method= 1
Volume Change Method= 0
XS Weighting Method= 0
Number of US Weighted Cross Sections= 1
Number of DS Weighted Cross Sections= 1
Upstream XS Weight=0.25
Main XS Weight=0.5
Downstream XS Weight=0.25
Number of DS XS's Weighted with US Boundary= 1
Upstream Boundary Weight= 1
Weight of XSs Associated with US Boundary= 0
Number of US XS's Weighted with DS Boundary= 1
Downstream Boundary Weight= 0.5
Weight of XSs Associated with DS Boundary= 0.5
Sediment Output Level= 4
Mass or Volume Output= 0
Output Increment Type= 1
Profile and TS Output Increment= 10
XS Output Flag= 0
XS Output Increment= 10
Disregard all LS=0
Disregard all Conn=0
Disregard all Breaches=0
Disregard all Pumps=0

--- UnnamedTribToEvitts.f01 (steady flow) ---

Flow Title=UnnamedTribToEvittsRun
Program Version=4.10
Number of Profiles= 1
Profile Names=1PCT
River Rch & RM=UNT1EvittsRn,Reach1          ,6877.351
     631
River Rch & RM=UNTribEvittsRn,Reach1          ,6115.208
     493
Boundary for River Rch & Prof#=UNT1EvittsRn,Reach1          , 1
Up Type= 0
Dn Type= 3
Dn Slope=0.00742
Boundary for River Rch & Prof#=UNTribEvittsRn,Reach1          , 1
Up Type= 0
Dn Type= 1
Dn Known WS=519
DSS Import GetInterval= 0
DSS Import GetPeak= 0
DSS Import FillOption= 0

--- UnnamedTribToEvitts.g01 (geometry) ---

Geom Title=UnnamedTribToEvitssRun
Program Version=4.10

River Reach=UNTribEvittsRn  ,Reach1
Reach XY= 30
2424606.05031344303153.5159920162424506.60464619302823.798147514
 2424390.6891956302738.4820451892424346.22045253302560.281614184
2424272.60937928302493.6150808482424181.21947019302177.722668022
 2424146.6896836302132.5849630242423983.72052136302083.892803192
 2423962.8872297302043.6149965972423942.74849044301825.559658438
2424044.83161961301770.6985476912424039.70991069 301746.93350336
2423717.74828428301381.8095616852423681.80380236301185.637381852
2423523.30379127300940.8373465242423504.55382878300838.059664935
2423564.07437903300755.991259515 2423596.2206402 300579.03163968
2423649.09914336300506.0964180982423667.74838428300301.948532432
2423929.55396302300076.2541019322424085.10942619299740.837121859
2424351.77621569 299587.364987852424380.33029245299492.159141526
2424582.72490078299285.106077939 2424582.5651242299220.004502103
2424760.10938853299110.9761768582424709.41493611298802.642804027
2424685.42876361298278.3482489442424726.40374728298150.819960684

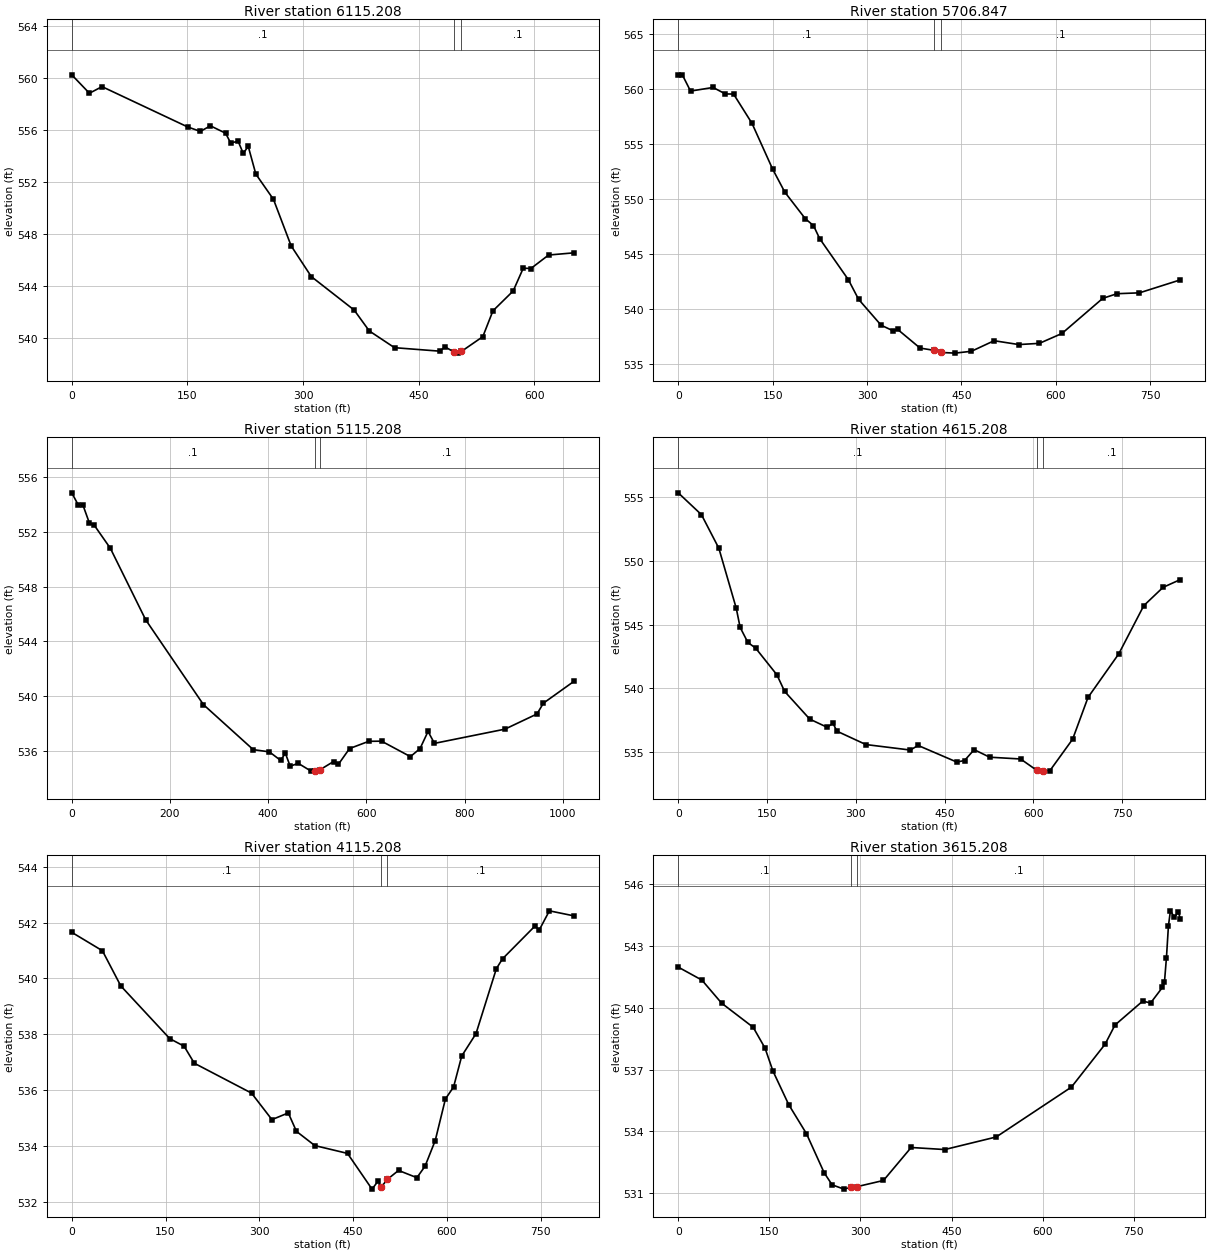
Type RM Length L Ch R = 1 ,6115.208,411.79,408.36,403.68
Node Name=978
XS GIS Cut Line= 3
2425068.63206545302963.7296261942424605.08509228303151.764355108
2424465.31863953303208.459779769
#Sta/Elev= 30
       0  560.27   22.89  558.85   39.23  559.36   150.4  556.25  166.74  555.91
  179.82  556.34  199.44  555.77  205.98  555.03  215.79  555.14  222.33  554.22
  228.86  554.75  238.67  552.62  261.56  550.67  284.45  547.09   310.6  544.72
  366.18  542.14   385.8  540.53   418.5  539.24  477.35  538.97  483.89   539.3
  495.19  538.93  500.23  538.82  505.21  538.95  533.02  540.09  546.14  542.08
  572.37  543.61  585.48  545.37  595.32  545.34  618.27  546.38  651.06  546.55
#Mann= 3 , 0 , 0
       0      .1       0  495.19    .045       0  505.21      .1       0
Bank Sta=495.19,505.21
XS Rating Curve= 0 ,0
Exp/Cntr=0.3,0.1

Type RM Length L Ch R = 1 ,5706.847,580.42,591.64,599.71
Node Name=979
XS GIS Cut Line= 4
2424811.26512611 302561.020129772424476.30057295302774.523639768
2424310.86816102302879.9689669312424300.65328644 303083.97216785
#Sta/Elev= 30
       0  561.27    6.51  561.32   19.54  559.84   55.35  560.17   74.89  559.58
   87.91  559.57  117.21   556.9  149.77  552.76  169.31  550.64  201.87  548.22
  214.89  547.59  224.66  546.41  270.24  542.67  286.52  540.88  322.34  538.52
  341.87     538  348.38  538.15   384.2  536.44  406.85  536.23  418.22  536.04
  439.73  535.98  465.88  536.15  501.85  537.11  541.09  536.76  573.78  536.87
  609.61  537.77  674.46  540.97  697.15  541.39  732.82  541.47  797.66  542.65
#Mann= 3 , 0 , 0
       0      .1       0  406.85    .045       0  418.22      .1       0
#XS Ineff= 2 , 0
       0                     515       0
Permanent Ineff=
       F       F
Bank Sta=406.85,418.22
XS Rating Curve= 0 ,0
Exp/Cntr=0.3,0.1

Type RM Length L Ch R = 1 ,5115.208,496.79,500,498.02
Node Name=980
XS GIS Cut Line= 3
2424701.79487261 302182.808287772424211.93495995302284.758871272
2423700.89628387302391.117254347
#Sta/Elev= 30
       0  554.86   13.08  553.98   22.89  553.95   35.97  552.64   45.78  552.49
   78.49  550.81  150.43  545.58  268.16  539.37  369.54  536.08  402.25  535.92
  425.14   535.3  434.95  535.81  444.76  534.87  461.11  535.08  487.27  534.51
  494.56  534.52  504.54  534.59  532.98  535.21  542.77     535   565.6  536.16
  604.75  536.69  630.85   536.7  689.58  535.57  709.15  536.16  725.46  537.41
  738.51  536.54  882.06  537.58  947.31  538.69  960.36  539.48 1022.34  541.07
#Mann= 3 , 0 , 0
       0      .1       0  494.56    .045       0  504.54      .1       0
#XS Ineff= 2 , 0
       0                     616       0
Permanent Ineff=
       F       F
Bank Sta=494.56,504.54
XS Rating Curve= 0 ,0
Exp/Cntr=0.3,0.1

Type RM Length L Ch R = 1 ,4615.208,514.65,500,463.7
Node Name=981
XS GIS Cut Line= 3
2424546.17412086301814.7699818462423946.25143619301932.068303689
2423713.45957895301977.584288776
#Sta/Elev= 30
       0  555.31   39.23   553.6   68.65  550.97   98.07  546.27   104.6  544.78
  117.68   543.6  130.76  543.16  166.71  541.07  179.79  539.77  222.28   537.6
   251.7  536.96  261.51  537.28  268.05  536.66  317.08  535.61  392.27  535.18
  405.34  535.54  470.72  534.24   483.8  534.36  500.14  535.21  526.29  534.62
  578.59  534.48  605.67   533.6  616.93  533.54  627.53  533.53  666.52  536.03
  692.52   539.3   744.5  542.71  786.75  546.48  819.24  547.91  848.48  548.52
#Mann= 3 , 0 , 0
       0      .1       0  605.67    .045       0  616.93      .1       0
#XS Ineff= 2 , 0
       0     419                       0
Permanent Ineff=
       F       F
Bank Sta=605.67,616.93
XS Rating Curve= 0 ,0
Exp/Cntr=0.3,0.1

Type RM Length L Ch R = 1 ,4115.208,491.32,500,507.35
Node Name=982
XS GIS Cut Line= 3
2424233.96247494301213.5943469412423876.45269127301562.948635101
2423659.57221952301774.881282106
#Sta/Elev= 30
       0  541.65   49.01  540.99   78.41  539.73  156.82  537.84  179.69  537.57
  196.02  536.96   287.5  535.89  320.17  534.94  346.31  535.18  359.38  534.52
  388.78  534.01  441.05  533.73  480.26  532.45  490.06  532.74  494.87  532.52
  504.86   532.8  522.69  533.12  552.03  532.86  565.07  533.27  581.38  534.19
  597.68  535.68  610.72  536.11  623.77  537.22  646.59  538.02   679.2  540.35
  688.98   540.7  741.15  541.88  747.67  541.73  763.97  542.42   803.1  542.24
#Mann= 3 , 0 , 0
       0      .1       0  494.87    .045       0  504.86      .1       0
Bank Sta=494.87,504.86
XS Rating Curve= 0 ,0
Exp/Cntr=0.3,0.1

Type RM Length L Ch R = 1 ,3615.208,477.19,500,519.25
Node Name=983
XS GIS Cut Line= 4
2423910.31384403300993.0383576012423658.51185419301134.988204941
2423513.88090986301216.5221626012423525.91369419301587.878375277
#Sta/Elev= 30
       0  541.97   38.97  541.34   71.45  540.22  123.42  539.05   142.9  538.04
   155.9  536.93  181.88   535.3  211.11  533.89  240.34  531.99  253.33  531.41
  272.82   531.2  283.86  531.29  294.31  531.32  337.89  531.62  383.47  533.22
  438.81  533.12  523.53  533.73  647.38  536.15  702.79  538.23  719.08  539.16
  764.71  540.32  777.75  540.23  797.31  540.99  800.57  541.25  803.82  542.43
  807.08  543.97  810.34   544.7  816.86  544.39  823.38  544.64  826.64  544.32
#Mann= 3 , 0 , 0
       0      .1       0  283.86    .045       0  294.31      .1       0
#XS Ineff= 2 , 0
       0                     421       0
Permanent Ineff=
       F       F
Bank Sta=283.86,294.31
XS Rating Curve= 0 ,0
Exp/Cntr=0.3,0.1

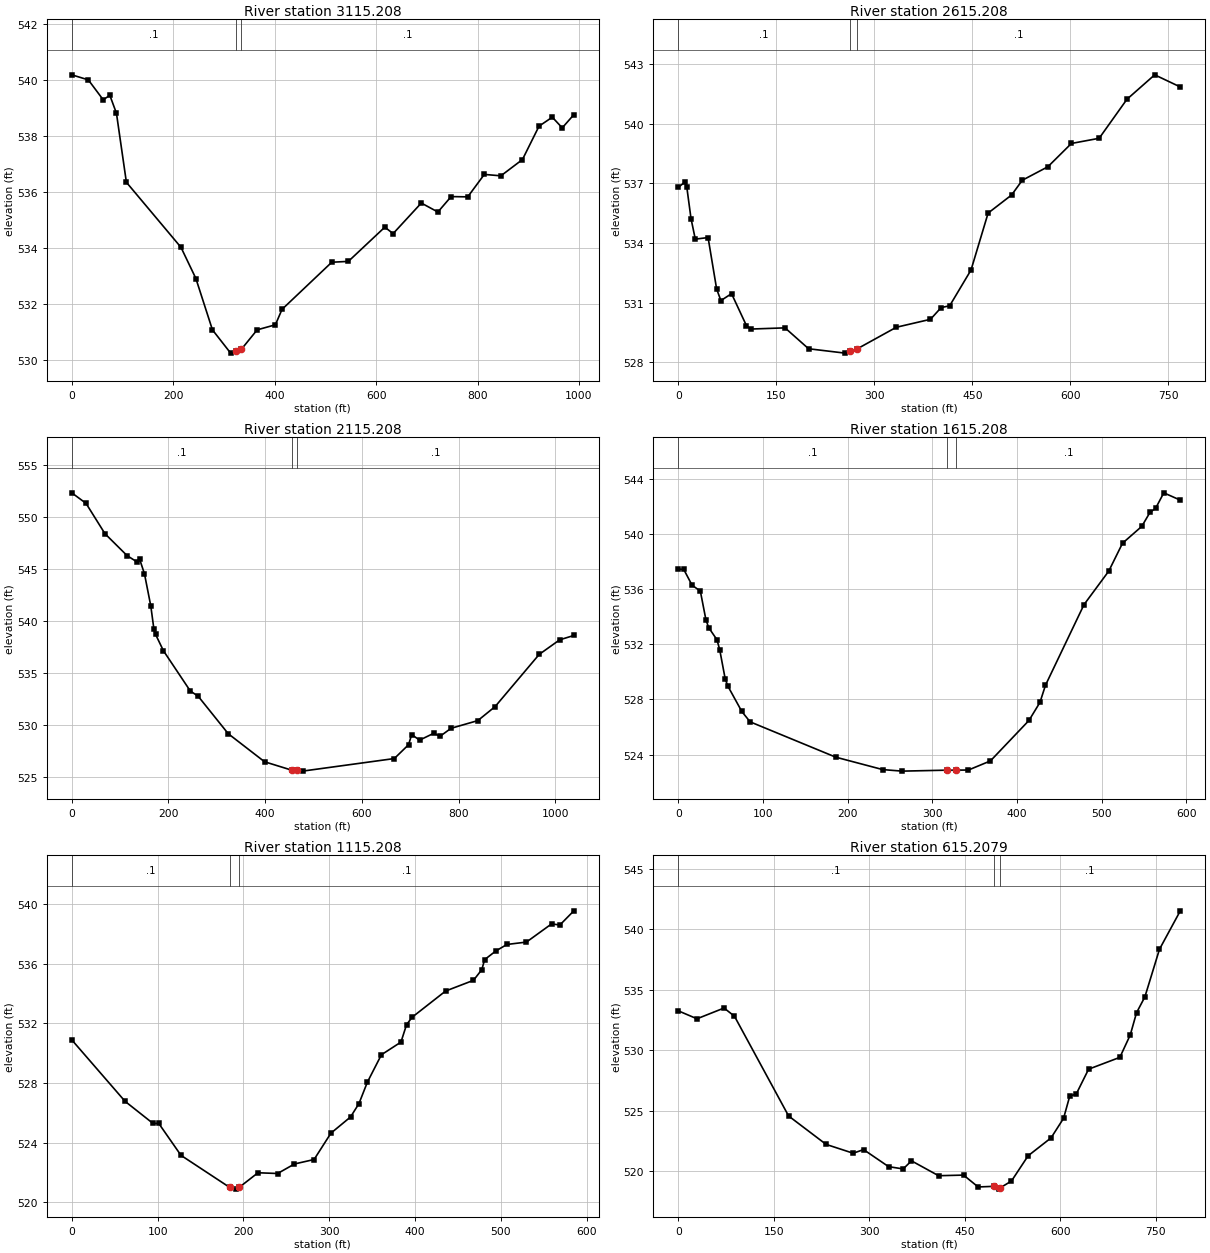
Type RM Length L Ch R = 1 ,3115.208,487.02,500,510.45
Node Name=984
XS GIS Cut Line= 3
2423900.30959894300768.3744368552423575.83682269300710.918843105
2422925.65341178300595.691055194
#Sta/Elev= 30
       0  540.18   32.63     540   61.99  539.29   75.04  539.45   88.09  538.81
  107.67  536.35  215.33  534.03  244.69  532.92  277.32  531.09  313.21  530.26
  324.53  530.32  334.54   530.4  365.48  531.09  401.44  531.27  414.51  531.82
  512.58   533.5  545.27  533.53  617.18  534.75  633.53  534.52   689.1  535.61
  721.79  535.29  747.94  535.84  780.63  535.83  813.32  536.63     846  536.58
   888.5  537.16  921.19  538.35  947.34  538.67  966.95  538.29  989.83  538.76
#Mann= 3 , 0 , 0
       0      .1       0  324.53    .045       0  334.54      .1       0
Bank Sta=324.53,334.54
XS Rating Curve= 0 ,0
Exp/Cntr=0.3,0.1

Type RM Length L Ch R = 1 ,2615.208,500.03,500,499.04
Node Name=985
XS GIS Cut Line= 4
2423847.52853653300440.7432023582423850.61809728300336.397610515
2423712.71548595300247.8200317772423292.09001486299977.644719109
#Sta/Elev= 30
       0   536.8    9.79  537.06   13.05  536.83   19.57  535.23    26.1   534.2
   45.67  534.28   58.72   531.7   65.24  531.11   81.56  531.46  104.39  529.85
  110.95  529.68   163.4  529.74  199.45  528.69  255.18  528.47  263.06  528.58
  273.57  528.68  333.64  529.77  385.92  530.17  402.26  530.76  415.33  530.85
     448  532.65  474.14  535.51  510.08  536.42  526.42  537.16  565.63  537.84
  601.57  539.01  644.05  539.27  686.53  541.23     729  542.46  768.21  541.85
#Mann= 3 , 0 , 0
       0      .1       0  263.06    .045       0  273.57      .1       0
Bank Sta=263.06,273.57
XS Rating Curve= 0 ,0
Exp/Cntr=0.3,0.1

Type RM Length L Ch R = 1 ,2115.208,500.88,500,491.97
Node Name=986
XS GIS Cut Line= 4
2424414.18258694300110.4626949432424019.44814019299872.819797516
2423820.35536252299752.9598010182423479.03878795299702.461870521
#Sta/Elev= 30
       0  552.36   29.41  551.35   68.62  548.43  114.37  546.32  133.98  545.74
  140.51  545.95  150.32  544.57  163.39  541.48  169.92  539.22  173.19  538.75
  189.53  537.17  245.08   533.3  261.42  532.79   323.5  529.19  398.66  526.49
  454.95  525.68  465.25  525.69  477.11  525.59  666.95   526.8  696.39  528.13
   702.9  529.11  719.18  528.57  748.47  529.23  761.49  528.94  784.28  529.71
  839.61  530.45  875.42   531.8  966.56  536.82 1008.88  538.22 1038.17  538.64
#Mann= 3 , 0 , 0
       0      .1       0  454.95    .045       0  465.25      .1       0
Bank Sta=454.95,465.25
XS Rating Curve= 0 ,0
Exp/Cntr=0.3,0.1

Type RM Length L Ch R = 1 ,1615.208,493.54,500,499.61
Node Name=987
XS GIS Cut Line= 3
2424637.76022378299689.7952291822424348.26900485299546.176093847
2424106.65925185299426.311176106
#Sta/Elev= 30
       0  537.44    6.53  537.42   16.32  536.28   26.11  535.85   32.64  533.79
   35.91  533.21    45.7  532.33   48.96  531.61   55.49  529.48   58.76  528.95
   75.08  527.13   84.87  526.38  186.06  523.82  241.55  522.92   264.4  522.81
   317.8  522.88   328.4  522.88  342.66  522.89  368.65  523.55  414.14  526.48
  427.14  527.79  433.64  529.03  479.13  534.87  508.38   537.3  524.63  539.32
  547.37  540.54  557.12  541.56  563.62  541.84  573.37  542.97  592.87  542.44
#Mann= 3 , 0 , 0
       0      .1       0   317.8    .045       0   328.4      .1       0
Bank Sta=317.8,328.4
XS Rating Curve= 0 ,0
Exp/Cntr=0.3,0.1

Type RM Length L Ch R = 1 ,1115.208,516.44,500,480.48
Node Name=988
XS GIS Cut Line= 5
2424755.25408328299327.0279100982424702.50484495 299218.23186785
2424643.20411052299181.1810889392424493.49706087299087.644530609
2424458.03190869 298872.86116752
#Sta/Elev= 30
       0   530.9   62.09  526.77   94.77  525.28   101.3  525.29  127.27  523.14
  183.91  520.99  190.83  520.87  194.94  520.98  216.99  521.97  239.87  521.92
  259.48  522.56  282.36  522.86  301.98  524.63  324.86  525.72  334.67  526.62
  344.48  528.06  360.82   529.9   383.6  530.75   390.1  531.92   396.6  532.42
  435.59  534.18  468.08   534.9  477.83  535.62  481.08  536.29  494.07  536.87
  507.07  537.31  529.81  537.47  559.06  538.69   568.8  538.62  585.05  539.57
#Mann= 3 , 0 , 0
       0      .1       0  183.91    .045       0  194.94      .1       0
Bank Sta=183.91,194.94
XS Rating Curve= 0 ,0
Exp/Cntr=0.3,0.1

Type RM Length L Ch R = 1 ,615.2079,610.6,613.77,616.63
Node Name=989
XS GIS Cut Line= 3
2425208.96347769298719.8552399432424710.13639136 298758.92701219
2424422.95947227298781.420733601
#Sta/Elev= 30
       0  533.27   29.43  532.61   71.95   533.5    88.3  532.82  173.33  524.57
  232.19  522.22   274.7  521.49  291.06  521.79   330.3  520.38  353.19  520.19
  366.27  520.86  408.79  519.63  448.03  519.68  470.92   518.7  495.35  518.75
  503.63  518.52  505.36  518.62  523.27  519.19  549.46  521.28  585.46  522.76
   605.1  524.38  614.92  526.24  624.74  526.36  644.38  528.44  693.48  529.42
  709.85  531.28  719.67  533.11  732.76  534.42  755.68  538.36  788.41  541.54
#Mann= 3 , 0 , 0
       0      .1       0  495.35    .045       0  505.36      .1       0
Bank Sta=495.35,505.36
XS Rating Curve= 0 ,0
Exp/Cntr=0.3,0.1

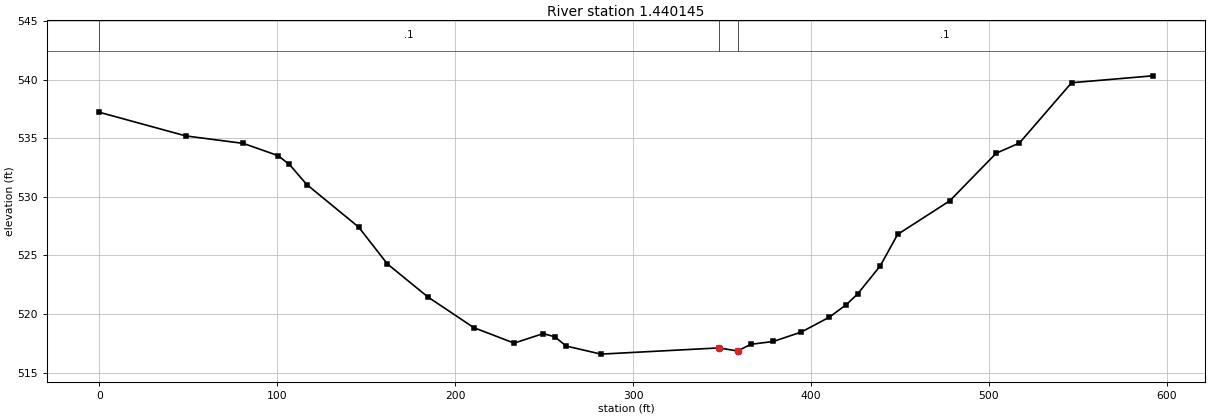
Type RM Length L Ch R = 1 ,1.440145,1.92,1.44,15.05
Node Name=990
XS GIS Cut Line= 5
2425063.58745611298240.9165652692424839.83626319298155.136881188
2424725.93163536298152.1805222632424643.89505403298150.031904519
2424499.65682544298089.462143764
#Sta/Elev= 30
       0  537.22   48.57   535.2   80.96  534.56  100.39  533.52  106.86  532.76
  116.58  531.05  145.72  527.42  161.91  524.27  184.58  521.46  210.49  518.83
  233.15  517.51   249.4  518.32  255.91  518.06  262.42  517.26  281.95  516.57
  348.15   517.1  358.78  516.84   366.2  517.41  378.82  517.65  394.61  518.46
  410.39  519.73  419.86   520.8  426.17   521.7   438.9   524.1  448.67  526.79
  478.01  529.66  504.08  533.72  517.12  534.59  546.45  539.74  592.08  540.33
#Mann= 3 , 0 , 0
       0      .1       0  348.15    .045       0  358.78      .1       0
Bank Sta=348.15,358.78
XS Rating Curve= 0 ,0
Exp/Cntr=0.3,0.1

River Reach=UNT1EvittsRn    ,Reach1
Reach XY= 30
2428217.08574228 283663.337124692428514.48147294283532.607727349
2428794.16923377283455.5245481882429163.96081702283141.982852444
2429242.08566077282956.0452321922429614.48156953 282706.56607236
 2429953.4795792282546.8866016862430116.39132686282553.614934683
2430217.90818419282487.6531243472430249.03016919282516.462121859
2430384.44689311282466.1147816032430553.19688369 282489.72595486
2430743.47471836282291.809355929 2430942.6527977282257.314674273
2431154.93288495 282073.059137272432043.12763086281654.656430766
2432144.82427786281568.7960381812432195.21066003281589.031562015
2432252.50254019 281517.850930112432220.55805027281481.392669693
2432230.62758394 281427.92033568 2432379.2385072 281328.96187219
2432626.80756585281096.4918646812432790.63597836281055.801985443
2432817.71925752280948.5102052692432756.78204344 280776.63522093
2432769.80268669280637.0518386812432801.57362053280558.926994935
 2432903.6567497280485.4894777692433060.42776161280102.676923186

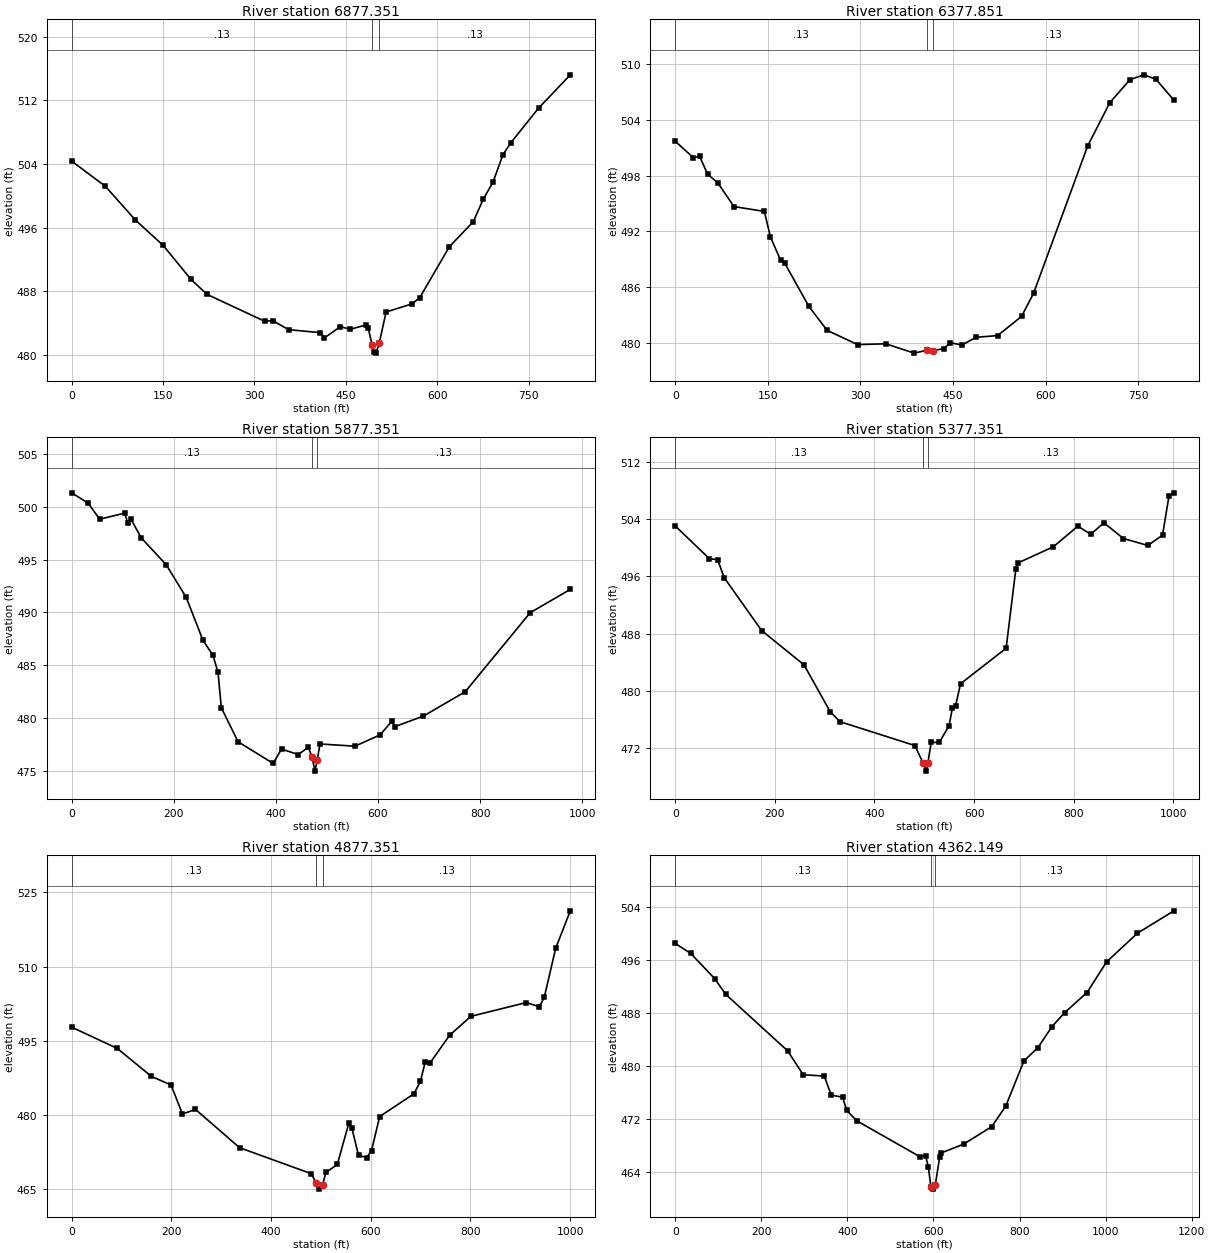
Type RM Length L Ch R = 1 ,6877.351,495.24,499.5,501.56
Node Name=966
XS GIS Cut Line= 3
2428346.62583752284145.8174589432428218.97156528283662.671443596
2428137.59738418283354.685839102
#Sta/Elev= 30
       0  504.38   55.53   501.2  104.52  496.98  150.24  493.78  195.97   489.5
   222.1  487.63  316.82  484.24  329.88  484.33  356.01  483.19  408.27  482.81
  414.81  482.15  440.94  483.57  457.27  483.24   483.4  483.79  486.66   483.4
  493.19  481.23  496.46  480.42  499.73  480.24  504.75   481.5  515.98  485.41
  558.24  486.42  571.24  487.22     620  493.63     659  496.75  675.26  499.56
  691.51  501.75  707.76  505.18  720.76  506.69  766.27  511.04  818.28  515.22
#Mann= 3 , 0 , 0
       0     .13       0  493.19    .045       0  504.75     .13       0
Bank Sta=493.19,504.75
XS Rating Curve= 0 ,0
Exp/Cntr=0.3,0.1

Type RM Length L Ch R = 1 ,6377.851,517.53,500.5,481.46
Node Name=967
XS GIS Cut Line= 5
2428817.63375378283871.6772591922428701.05393444283607.658430263
 2428678.3817357 283485.225932362428658.34535845283361.824932441
2428501.87847978283142.510738522
#Sta/Elev= 30
       0   501.7   29.52  499.92   39.36   500.1   52.48  498.15   68.87  497.23
   95.11  494.67  144.31  494.15  154.15  491.42  170.54  488.91   177.1  488.61
  216.46  483.93  245.98  481.36  295.17  479.83  341.04  479.91  386.91  478.91
  407.89  479.23  417.83  479.19  435.56   479.4  445.18  480.03  464.42  479.78
  486.85  480.61  522.12   480.8  560.86  482.86  580.34  485.36  667.98  501.21
  703.68  505.84  736.14  508.31  758.86  508.84  778.34  508.37  807.55  506.11
#Mann= 3 , 0 , 0
       0     .13       0  407.89    .045       0  417.83     .13       0
Bank Sta=407.89,417.83
XS Rating Curve= 0 ,0
Exp/Cntr=0.3,0.1

Type RM Length L Ch R = 1 ,5877.351,494.35,500,504.24
Node Name=968
XS GIS Cut Line= 4
2429329.01101185283593.3372646872429322.84862261283460.653146848
2429083.51150286283214.0201099372428735.26252744282855.155014023
#Sta/Elev= 30
       0  501.32    32.4  500.35   55.07  498.82  103.67   499.4  110.15  498.47
  116.63   498.8   136.1  497.07   185.2  494.52  224.47  491.42   257.2  487.36
  276.84  485.94  286.66  484.33  293.21  480.98  325.94  477.76  394.67  475.71
  411.04  477.07  443.77  476.55  463.41  477.23  470.97   476.3   476.5  474.98
  480.98  476.02   486.3  477.55  554.94  477.34  603.97  478.41  626.84  479.68
  633.38   479.2  688.94  480.19  770.65  482.49  898.12  489.98  976.56  492.18
#Mann= 3 , 0 , 0
       0     .13       0  470.97    .045       0  480.98     .13       0
Bank Sta=470.97,480.98
XS Rating Curve= 0 ,0
Exp/Cntr=0.3,0.1

Type RM Length L Ch R = 1 ,5377.351,493.14,500,503.99
Node Name=969
XS GIS Cut Line= 3
2429678.30427653283262.9534110132429394.53056586282850.399118021
2429110.97339019282438.159785017
#Sta/Elev= 30
       0  503.03   68.73  498.44   85.09  498.33   98.18  495.82  173.45  488.42
  258.55  483.63  310.91  477.11  330.55   475.7  481.09  472.36  497.46  469.94
     504  468.79  507.27  469.97  513.81  472.81  530.16   472.8  549.78  475.15
  556.32  477.58  562.86  477.94  572.67  480.99  664.24  485.95  683.86  497.07
  687.13  497.83  759.08  500.12  808.13  502.99  834.29  501.86  860.46  503.47
   899.7  501.27  948.75   500.3  978.18  501.74  991.26  507.25 1001.08  507.65
#Mann= 3 , 0 , 0
       0     .13       0  497.46    .045       0  507.27     .13       0
Bank Sta=497.46,507.27
XS Rating Curve= 0 ,0
Exp/Cntr=0.3,0.1

Type RM Length L Ch R = 1 ,4877.351,493.54,515.2,504.5
Node Name=970
XS GIS Cut Line= 3
2430029.83802228283062.0086029322429824.86960019282605.624017015
2429620.00058736282149.461215436
#Sta/Elev= 30
       0  497.75   91.56  493.44  160.23  487.77  199.47  486.04  222.35  480.17
  248.51   481.1   336.8  473.36  480.68   468.1  490.49  466.24  497.03  464.97
  503.57  465.88   510.1  468.34  532.98  469.96  555.86  478.25   562.4  477.24
  575.47   471.8  591.81  471.36  601.62  472.78  617.96  479.66  686.59  484.25
  699.67  486.78  709.47  490.78  719.28  490.55   758.5  496.13  800.98  499.93
  912.11  502.72  938.25  501.87  948.06  503.76  970.94  513.69 1000.35  521.28
#Mann= 3 , 0 , 0
       0     .13       0  490.49    .045       0  503.57     .13       0
Bank Sta=490.49,503.57
XS Rating Curve= 0 ,0
Exp/Cntr=0.3,0.1

Type RM Length L Ch R = 1 ,4362.149,493.8,484.8,470.66
Node Name=971
XS GIS Cut Line= 5
2430434.26273836283080.5335002692430332.64286286282722.268468767
 2430270.5498112282512.2403455232430223.30253036282352.427344933
2430295.37390852281958.311335266
#Sta/Elev= 30
       0  498.44   35.93  496.94   91.47  493.14   117.6  490.74  261.33  482.22
  297.26  478.63  346.27  478.42   362.6  475.54  388.74  475.24  398.55  473.24
  421.43  471.69  568.53  466.25  581.61  466.41  588.14  464.73  594.25  461.63
  597.95  461.36  604.14  461.94  614.29  466.15  617.55  466.81  669.84  468.14
  735.19  470.78  767.84  473.87  810.18   480.7  842.75  482.72  875.33  485.88
  904.64  487.99  956.76  491.03 1002.36  495.66 1074.02  499.99 1158.72  503.36
#Mann= 3 , 0 , 0
       0     .13       0  594.25    .045       0  604.14     .13       0
Bank Sta=594.25,604.14
XS Rating Curve= 0 ,0
Exp/Cntr=0.3,0.1

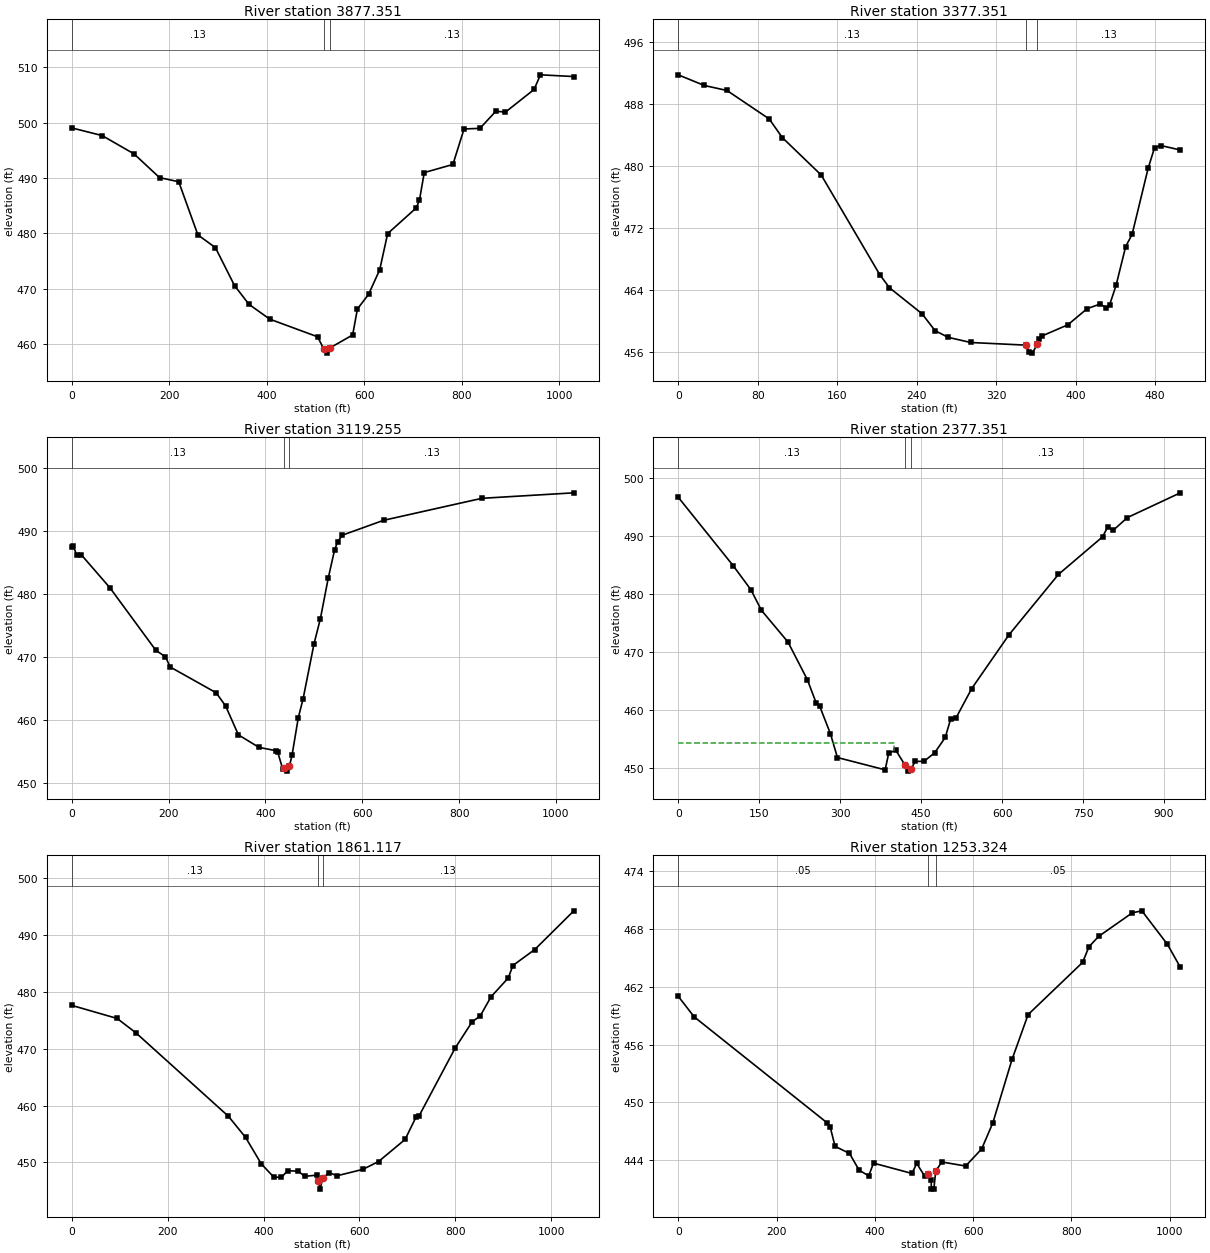
Type RM Length L Ch R = 1 ,3877.351,480,500,481.88
Node Name=972
XS GIS Cut Line= 3
2430986.45454736282771.2332658472430670.55262011282353.086136267
2430365.46956886281949.259516105
#Sta/Elev= 30
       0  499.04   62.23  497.66  127.74  494.35  180.15  490.06  219.45  489.32
  258.76  479.72  294.78  477.41  334.09  470.54  363.57  467.18  406.15   464.5
  504.41  461.31  517.17  459.09  524.06  458.36  529.46  459.29  576.31  461.64
   586.1  466.34  608.96  468.97  631.82  473.41  648.14  479.95  706.92   484.6
  713.45  486.02  723.24  490.97  782.02  492.44  804.88  498.85  837.53  498.96
  870.18  502.06  889.77  501.89  948.55  505.98  961.61  508.63 1030.18  508.32
#Mann= 3 , 0 , 0
       0     .13       0  517.17    .045       0  529.46     .13       0
Bank Sta=517.17,529.46
XS Rating Curve= 0 ,0
Exp/Cntr=0.3,0.1

Type RM Length L Ch R = 1 ,3377.351,248.78,258.1,261.76
Node Name=973
XS GIS Cut Line= 3
2431285.17442235282434.2867612692431066.76770695282152.276826605
2430975.63960835282034.611379519
#Sta/Elev= 30
       0  491.73   26.18  490.36   49.09  489.71   91.63  486.04  104.72  483.65
  143.99  478.81  202.89  465.98  212.71  464.28  245.43  460.94  258.52  458.77
  271.61   457.9  294.52  457.23  350.15  456.89  353.42  456.01  356.69  455.86
  361.67  457.08  363.17  457.67   366.4  458.08  392.28  459.51   411.7  461.59
  424.64  462.18  431.11  461.73  434.34  462.08  440.81  464.58  450.52   469.6
  456.99  471.17  473.17  479.71  479.64  482.36  486.11  482.61  505.52  482.04
#Mann= 3 , 0 , 0
       0     .13       0  350.15    .045       0  361.67     .13       0
Bank Sta=350.15,361.67
XS Rating Curve= 0 ,0
Exp/Cntr=0.3,0.1

Type RM Length L Ch R = 1 ,3119.255,734.89,741.9,738.37
Node Name=974
XS GIS Cut Line= 5
2431362.73496278282456.2279903592431319.49292327282108.128292859
 2431261.4789317281998.9287081062431203.46658053281889.732732266
2430811.34630178281692.339098185
#Sta/Elev= 30
       0  487.49    3.28  487.62    9.83  486.15   19.67  486.19   78.68  480.97
  173.75  471.03  193.42  470.03  203.25   468.4  298.32  464.31  317.99  462.19
  344.22  457.64  386.57  455.66  422.36  455.12  425.62  454.86  435.38   452.3
  439.27  452.36  445.14  451.89  449.33  452.63   454.9  454.37  467.92  460.37
  477.68   463.3  500.46   472.1  513.48  476.04  529.75  482.48  542.76  486.92
  549.27  488.28  559.03   489.3  643.94  491.65  847.07  495.14 1037.08  496.01
#Mann= 3 , 0 , 0
       0     .13       0  439.27    .045       0  449.33     .13       0
Bank Sta=439.27,449.33
XS Rating Curve= 0 ,0
Exp/Cntr=0.3,0.1

Type RM Length L Ch R = 1 ,2377.351,516.41,516.23,437.24
Node Name=975
XS GIS Cut Line= 4
2432005.09621085282096.5056126862432037.99312669281932.490520775
2431924.19873486281700.2629668562431702.28546478281247.390513018
#Sta/Elev= 30
       0  496.69  101.68  484.92  134.48  480.79  154.16  477.22  203.29  471.77
   239.3  465.27  255.67  461.25  262.21  460.68  281.86  456.01  294.95  451.88
  383.33  449.76  389.88  452.61  402.98  453.15  420.55  450.53  425.89  449.54
  431.29  449.91  438.99  451.21  455.36  451.23  475.01  452.69  494.66  455.33
  504.49  458.44  514.31  458.64  543.78  463.76  612.55  472.98  704.25  483.39
  786.12  489.87  795.94  491.61  805.77  490.99  831.97  493.18  930.21  497.45
#Mann= 3 , 0 , 0
       0     .13       0  420.55    .045       0  431.29     .13       0
#XS Ineff= 2 , 0
          400.59  454.46
Permanent Ineff=
       F       F
Bank Sta=420.55,431.29
XS Rating Curve= 0 ,0
Exp/Cntr=0.3,0.1

Type RM Length L Ch R = 1 ,1861.117,565.74,607.79,620.85
Node Name=976
XS GIS Cut Line= 5
2432593.29057252281786.7834631062432335.77599569 281465.73128368
2432229.66892444281456.6469842642432143.93582819 281450.80053927
2431762.47694544281224.988654941
#Sta/Elev= 30
       0  477.58   94.73  475.28  133.92  472.75  326.64  458.12  362.57   454.4
  395.24  449.76  421.25  447.44  437.39  447.38  450.29  448.57  472.88  448.45
  485.79  447.56  511.61  447.78  513.72  446.82  518.06  445.32  523.71   447.3
  537.16  448.22  553.07  447.66  607.26  448.79  639.85  450.16  695.26  454.04
  718.08  457.97   724.6   458.2  799.56  470.06  835.42  474.73  851.71  475.68
  874.53  479.09  910.38  482.38  920.16  484.58  965.79  487.39 1047.28  494.18
#Mann= 3 , 0 , 0
       0     .13       0  513.72    .045       0  523.71     .13       0
Bank Sta=513.72,523.71
XS Rating Curve= 0 ,0
Exp/Cntr=0.3,0.1

Type RM Length L Ch R = 1 ,1253.324,485.37,478.81,438.79
Node Name=977
XS GIS Cut Line= 5
2432791.21110845 281545.932894932432835.02270061281338.886064932
2432662.72055177281085.744838938 2432648.9266161281065.506362349
2432348.94854152280691.839458764
#Sta/Elev= 30
       0  461.03   32.56  458.89  302.84  447.89  309.36  447.41  319.13  445.44
  348.45  444.71     368  442.97  387.54  442.38  397.32   443.7   475.5  442.63
  485.27  443.67  501.56  442.33  508.07  442.56  514.59  441.97     515     441
     520     441  523.97  442.88  536.22  443.82  584.72   443.4  617.31  445.17
  640.13  447.89  679.25  454.49  711.84  459.13  822.68  464.55  835.71  466.18
  855.27  467.25  923.73   469.7  943.29  469.91  995.44  466.42 1021.52  464.05
#Mann= 3 , 0 , 0
       0     .05       0  508.07    .045       0  523.97     .05       0
#XS Ineff= 2 , 0
       0     425                       0
Permanent Ineff=
       F       F
Bank Sta=508.07,523.97
XS Rating Curve= 0 ,0
Exp/Cntr=0.3,0.1

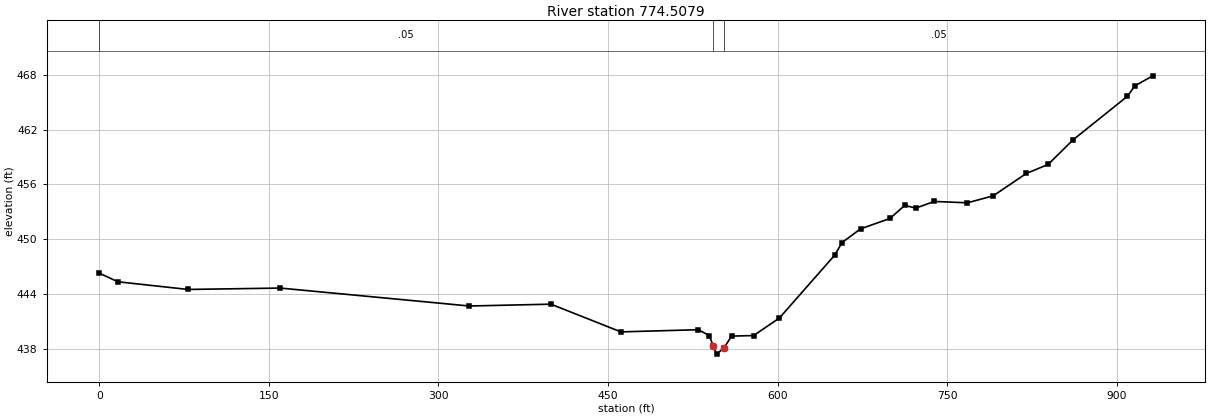
Type RM Length L Ch R = 1 ,774.5079,715.22,774.51,768.27
XS GIS Cut Line= 5
2432935.02348486281171.2630406022432938.54906836281001.406753019
2432916.05862777280776.2018228472432496.48203911280696.784002692
2432393.87791361280732.200598523
#Sta/Elev= 30
       0   446.3   16.34  445.36   78.41  444.52  160.09  444.67  327.34  442.71
  399.48  442.91  461.41  439.88  529.87  440.12  539.65  439.47  542.91  438.34
  546.17  437.45  552.69  438.16  559.21  439.42  578.76  439.48  601.58   441.4
  650.48  448.27     657  449.65   673.3  451.14  699.37  452.28  712.41  453.71
  722.19  453.41  738.49  454.14  767.83  453.99  790.65  454.75  819.99   457.2
  839.21  458.18  861.56   460.9  909.44  465.64  915.83  466.76  931.79  467.87
#Mann= 3 , 0 , 0
       0     .05       0  542.91    .045       0  552.69     .05       0
Bank Sta=542.91,552.69
XS Rating Curve= 0 ,0
Exp/Cntr=0.3,0.1
Stream Node=UNT1EvittsRn    ,Reach1          , 0 , 0 ,Upstream end
Stream Node=UNT1EvittsRn    ,Reach1          , 0 , 1 ,Downstream end
Stream Node=UNTribEvittsRn  ,Reach1          , 0 , 0 ,Upstream end
Stream Node=UNTribEvittsRn  ,Reach1          , 0 , 1 ,Downstream end

Chan Stop Cuts=-1
Use User Specified Reach Order=0
Composite Channel Slope=5